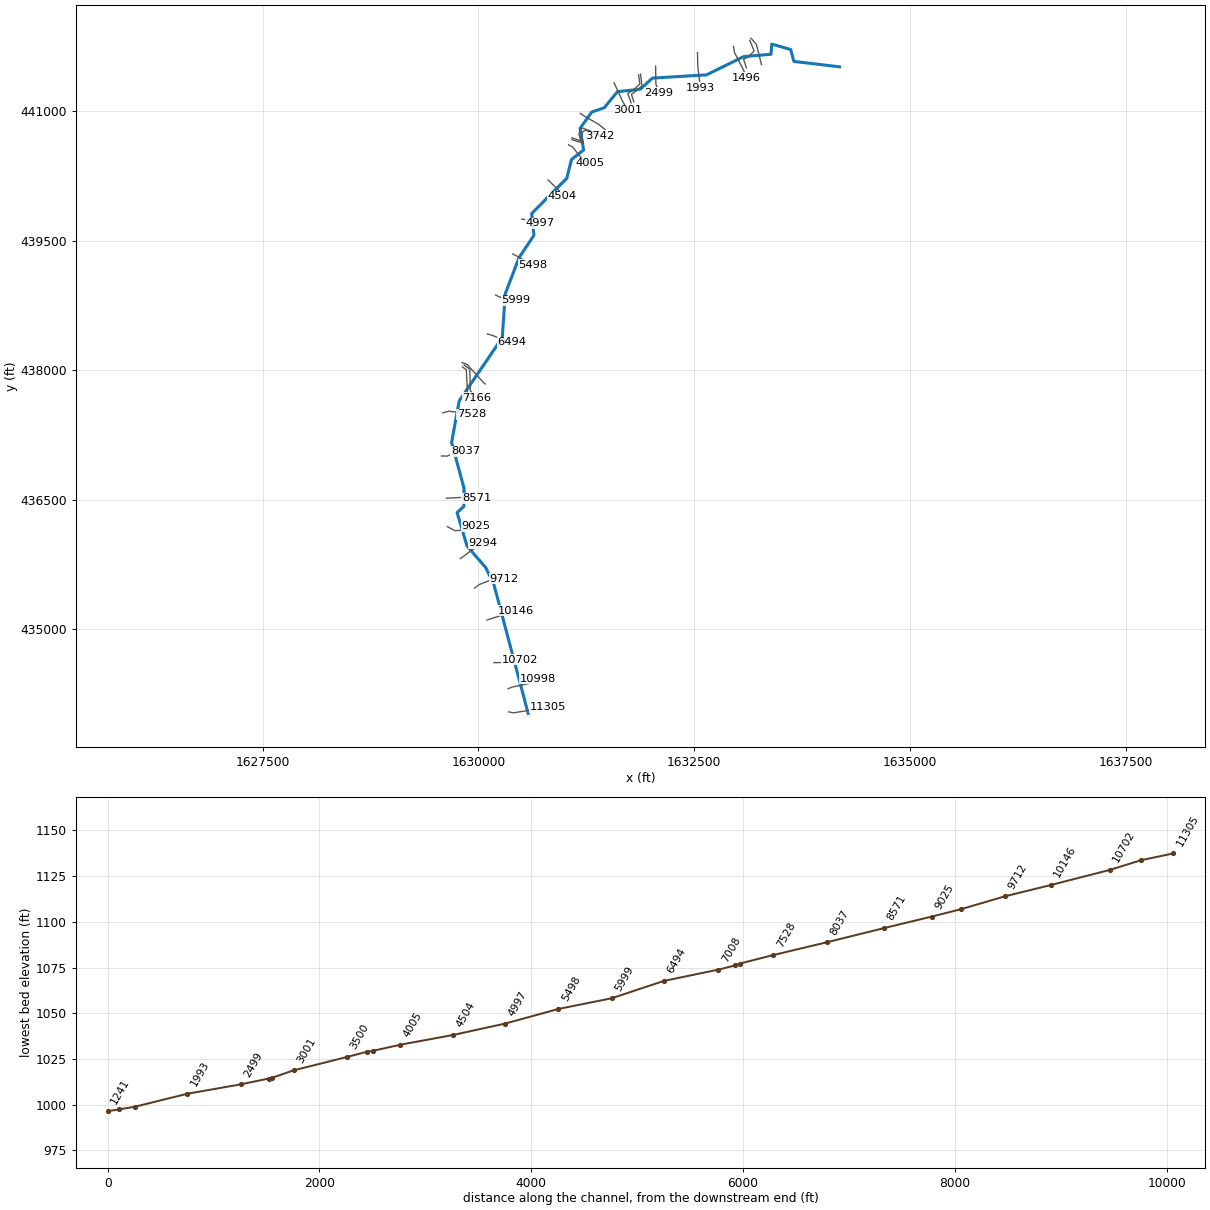
--- STEENERFK.prj (project) ---

Proj Title=STEENERFK
Current Plan=p01
Default Exp/Contr=0,0
English Units
Geom File=g01
Flow File=f01
Plan File=p01
BEGIN DESCRIPTION:
---------- MODELED AS PART OF WVEMD CTP PROGRAM, 2023----------
Stream Name: Steener Fork
Flood Zone:  AFH
Wetzel County, WV
HEC-RAS Version: RAS 6.3
Vertical Datum: NAVD88
Projection: NAD 1983 StatePlane West Virginia S FIPS 4702 (US Feet)
Terrain: 1-meter West Virginia FEMA R3 South Central (collected 2018-2020)
Land Use: 2019 NLCD
Hydrologic Method:
WV SIR2010-5033 regression equations
Additional Model Notes:
None
END DESCRIPTION:
DSS Export Rating Curves= 0
DSS Export Rating Curve Sorted= 0
DSS Export Volume Flow Curves= 0
DXF OffsetX= 0
DXF OffsetY= 0
DXF ScaleX= 0
DXF ScaleY= 0

--- STEENERFK.p01 (plan) ---

Plan Title=Floodplain
Program Version=6.30
Short Identifier=Floodplain
Geom File=g01
Flow File=f01
Subcritical Flow
K Sum by GR= 0
Std Step Tol= 0.01
Critical Tol= 0.01
Num of Std Step Trials= 20
Max Error Tol= 0.3
Flow Tol Ratio= 0.001
Split Flow NTrial= 30
Split Flow Tol= 0.02
Split Flow Ratio= 0.02
Log Output Level= 0
Friction Slope Method= 1
Unsteady Friction Slope Method= 2
Unsteady Bridges Friction Slope Method= 1
Parabolic Critical Depth
Global Vel Dist= 0 , 0 , 0
Global Log Level= 0
CheckData=False
Encroach Param=-1 ,0,0, 0
Mapping Interval=1HOUR
Computation Time Step Use Courant=        0
Computation Time Step Use Time Series=    0
Computation Time Step Count To Double=0
Computation Time Step Max Doubling=0
Computation Time Step Max Halving=0
Computation Time Step Residence Courant=0
Run HTab= 0
Run UNet= 0
Run Sediment= 0
Run PostProcess= 0
Run WQNet= 0
Run RASMapper=-1
UNET Theta= 0
UNET Theta Warmup= 0
UNET ZTol= 0
UNET ZSATol= 0
UNET MxIter= 0
UNET Max Iter WO Improvement= 0
UNET MaxInSteps= 0
UNET DtIC= 0
UNET DtMin= 0
UNET MaxCRTS= 0
UNET WFStab= 0
UNET SFStab= 0
UNET WFX= 1
UNET SFX= 1
UNET Gravity=32.17405
UNET 1D Methodology=Finite Difference
UNET DSS MLevel= 1
UNET Pardiso=0
UNET DZMax Abort= 0
UNET Use Existing IB Tables= 0
UNET Froude Reduction=False
UNET Froude Limit= 0
UNET Froude Power= 0
UNET D1 Cores= 0
UNET WindReference=Eulerian
UNET WindDragFormulation=Hsu (1988)
UNET D2 Coriolis=0
UNET D2 Cores= 0
UNET D2 Theta= 1
UNET D2 Theta Warmup= 1
UNET D2 Z Tol= 0.01
UNET D2 Volume Tol= 0.01
UNET D2 Max Iterations= 20
UNET D2 Equation= 0
UNET D2 RampUpFraction=0.1
UNET D2 TimeSlices= 1
UNET D2 Turbulence Formulation=Non-Conservative (original)
UNET D2 Eddy Viscosity=0.3
UNET D2 Transverse Eddy Viscosity=0.1
UNET D2 Smagorinsky Mixing=0
UNET D2 BCVolumeCheck=0
UNET D2 Cores=0
UNET D2 SolverType=PARDISO (Direct)
UNET D2 Minimum Iterations= 3
UNET D2 Maximum Iterations= 30
UNET D2 Restart Number= 10
UNET D2 Relaxation Coeff=1.3
UNET D2 SOR Precondition Iterations= 10
UNET D2 ILUT Maximum Fill= 8
UNET D2 ILUT Tolerance=1E-08
UNET D2 Convergence Tolerance=0.00001
UNET D1D2 MaxIter= 0
UNET D1D2 ZTol=0.01
UNET D1D2 QTol=0.1
UNET D1D2 MinQTol=1
Write IC File= 0
Write IC File at Fixed DateTime=0
Write IC File at Sim End=0
Echo Input=False
Echo Parameters=False
Echo Output=False
Write Detailed= 0
HDF Write Warmup=0
HDF Write Time Slices=0
HDF Flush=0
HDF Compression= 1
HDF Chunk Size= 1
HDF Spatial Parts= 1
HDF Use Max Rows=0
HDF Fixed Rows= 1
Calibration Method= 0
Calibration Iterations= 20
Calibration Max Change=0.05
Calibration Tolerance=0.2
Calibration Maximum=1.5
Calibration Minimum=0.5
Calibration Optimization Method= 1
WQ AD Non Conservative
WQ ULTIMATE=-1
WQ Max Comp Step=1HOUR
WQ Output Interval=15MIN
WQ Output Selected Increments= 0
WQ Output face flow=0
WQ Output face velocity=0
WQ Output face area=0
WQ Output face dispersion=0
WQ Output cell volume=0
WQ Output cell surface area=0
WQ Output cell continuity=0
WQ Output cumulative cell continuity=0
WQ Output face conc=0
WQ Output face dconc_dx=0
WQ Output face courant=0
WQ Output face peclet=0
WQ Output face adv mass=0
WQ Output face disp mass=0
WQ Output cell mass=0
WQ Output cell source sink temp=0
WQ Output nsm pathways=0
WQ Output nsm derived pathways=0
WQ Create Restart=0
WQ Fixed Restart=0
WQ System Summary=0
WQ Write To DSS=0
Sorting and Armoring Iterations= 10
XS Update Threshold= 0.02
Bed Roughness Predictor= 0
Hydraulics Update Threshold= 0.02
Energy Slope Method= 1
Volume Change Method= 1
Sediment Retention Method= 0
Sediment TS Multiplier= 1
Warm Up Method= 0
XS Weighting Method= 0
Number of US Weighted Cross Sections= 1
Number of DS Weighted Cross Sections= 1
Upstream XS Weight=0
Main XS Weight=1
Downstream XS Weight=0
Number of DS XS's Weighted with US Boundary= 1
Upstream Boundary Weight= 1
Weight of XSs Associated with US Boundary= 0
Number of US XS's Weighted with DS Boundary= 1
Downstream Boundary Weight= 0.5
Weight of XSs Associated with DS Boundary= 0.5
Percentile Method= 0
Sediment Output Level= 3
Mass or Volume Output= 0
Output Increment Type= 1
Profile and TS Output Increment= 1
Transport Output Increment 1
XS Output Flag= 0
XS Output Increment= 10
Read HDF5 Sediment Hotstart= 0
Sediment Hotstart Type= 0
Write Gradation File= 0
Read Gradation Hotstart= 0
Write HDF5 File= 1
Write Binary Output= 1
Write DSS Sediment File= 0
DSS Sediment Output Type= 1
SV Curve= 0
Specific Gage Flag= 0
Subcell Erosion Methods= 0
Subcell Deposition Methods= 0
Advection Scheme= 1
Matrix Solver= 0
Implicit Weighting Factor= 1
Maximum Outer Loop Convergence Iterations= 5
Convergence Maximum Absolute= 0.001
Convergence RMSE= 0.0001
Grain Fractions Max Abs Error= 0.001
Max Subgrid Regions= 1
Max Subgrid Length Scale= 3.402823E+38
Initial Layer Thickness= 3.402823E+38
Min Layer Thickness= 3.402823E+38
Max Layer Thickness= 3.402823E+38
Number of Layers= 5

--- STEENERFK.f01 (steady flow) ---

Flow Title=Flow
Program Version=6.30
Number of Profiles= 1
Profile Names=F01pct
River Rch & RM=STEENERFK,Main,11305
     352
River Rch & RM=STEENERFK,Main,10702
     413
River Rch & RM=STEENERFK,Main,9025
     474
River Rch & RM=STEENERFK,Main,7528
     533
River Rch & RM=STEENERFK,Main,6494
     594
River Rch & RM=STEENERFK,Main,4997
     738
River Rch & RM=STEENERFK,Main,2796
     871
Boundary for River Rch & Prof#=STEENERFK,Main            , 1
Up Type= 0
Dn Type= 3
Dn Slope=0.0075
DSS Import GetInterval= 0
DSS Import GetPeak= 0
DSS Import FillOption= 0

--- STEENERFK.g01 (geometry) ---

Geom Title=Geometry
Program Version=6.31

River Reach=STEENERFK       ,Main
Reach XY= 30
1630575.61076115434021.419019036 1630179.4236699435513.505365954
1630084.57305689 435710.708900341629866.76094588 435963.06053744
 1629752.6951615436349.1211018761629830.43568851 436422.36908586
1629832.63167166436631.9797564911629688.69410735437161.713485093
1629776.87246059437644.776292041     1630275.595      438378.047
     1630310.376      438887.549      1630469.87      439305.241
     1630642.524      439564.065     1630616.516      439817.563
      1631023.24      440225.227     1631077.136      440442.377
     1631218.142      440553.928     1631177.094      440804.919
     1631313.087      440994.494     1631455.973      441042.123
      1631610.14      441230.131     1631874.918      441258.646
     1632016.237      441387.431     1632641.364      441424.406
     1633074.253       441637.09     1633389.068      441663.529
     1633398.371      441781.034     1633617.714      441718.854
     1633654.101      441580.766      1634184.17       441517.93

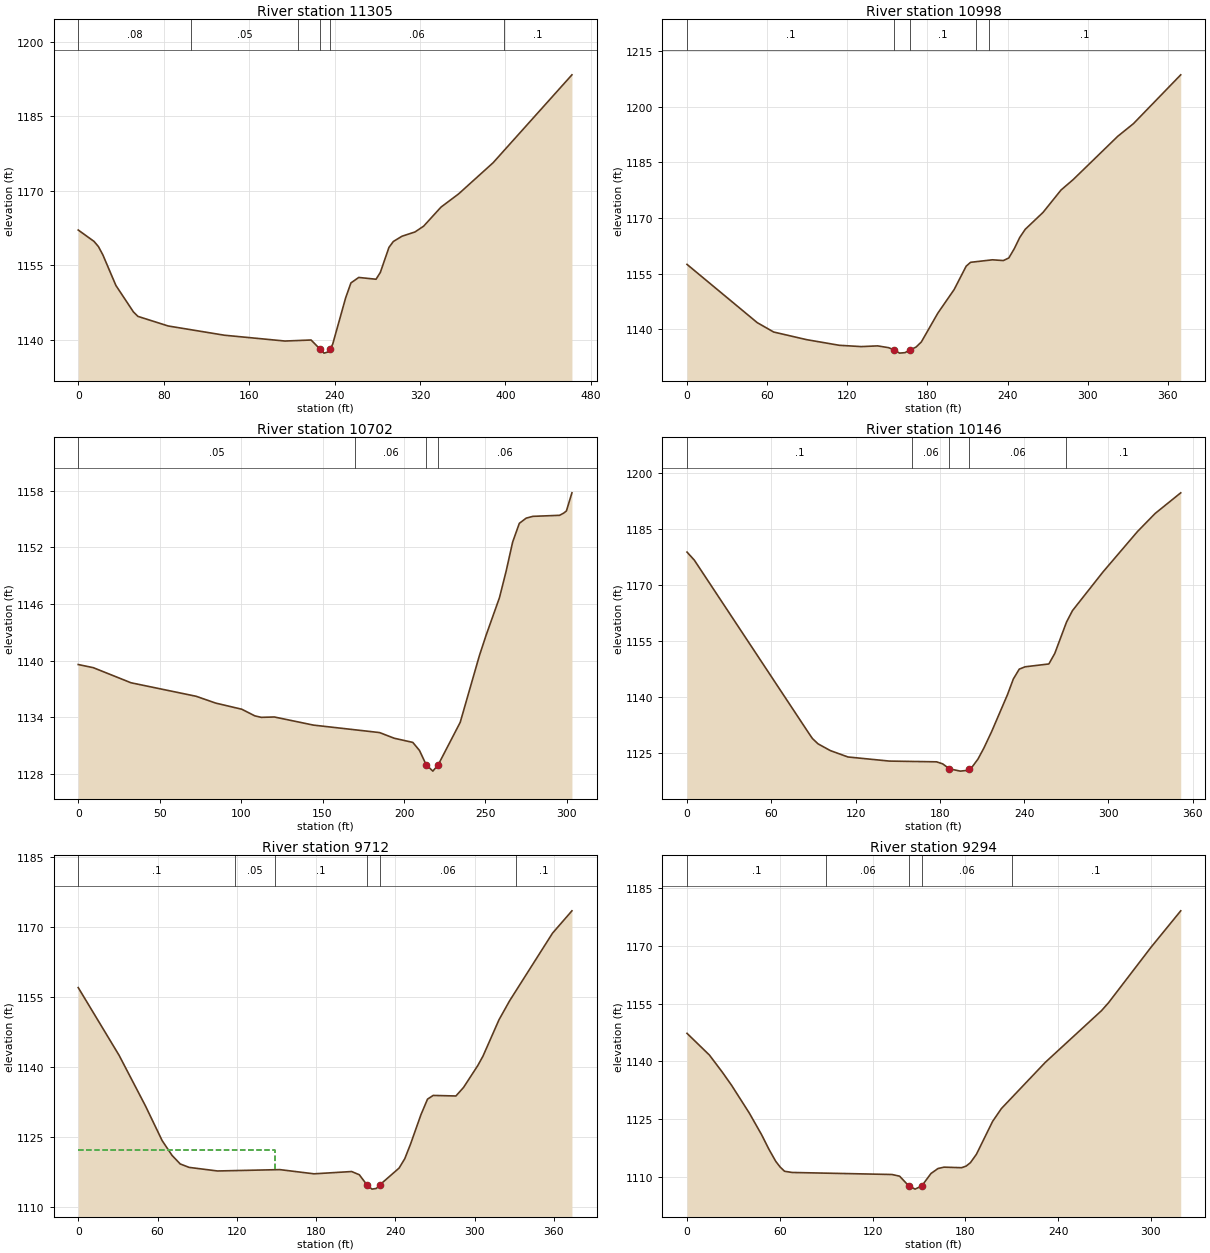
Type RM Length L Ch R = 1 ,11305   ,306.8,307.3,307.1
XS GIS Cut Line= 4
1630349.62378589 434039.09857355 1630404.2686374434027.145012283
1630692.86175943434074.9592573521630804.71293986434095.451076668
#Sta/Elev= 30
       0 1162.13    14.8 1159.84    18.9  1158.8      23 1157.16    35.3 1150.97
    51.7 1145.65    55.9 1144.76    84.2 1142.83   136.9 1140.97   193.6  1139.8
     218 1140.01   226.1 1138.24   230.1 1137.37   234.2 1137.62   235.8  1138.2
   238.2 1139.15   250.4 1148.52   255.3 1151.49   262.6 1152.59   278.8 1152.23
   282.8 1153.59   290.9 1158.63     295 1159.82   303.1 1160.88   315.3 1161.74
   323.4 1162.91   339.6 1166.73   356.1 1169.39   388.4 1175.66   462.2 1193.34
#Mann= 6 ,-1,0
       0     .08       0  105.94     .05       0  205.94     .06       0
   226.1    .045       0   235.8     .06       0  398.46      .1       0
Bank Sta=226.1,235.8
XS Rating Curve= 0 ,0
Exp/Cntr(USF)=0,0
Exp/Cntr=0.3,0.1

Type RM Length L Ch R = 1 ,10998   ,294.8,295.5,295.6
XS GIS Cut Line= 4
1630343.58952829 434306.409982841630385.75376557434325.149643851
1630590.71880787434369.6563387521630691.44448581434422.361635345
#Sta/Elev= 30
       0 1157.53    52.6 1141.83    64.9 1139.31    89.5 1137.26     114 1135.74
   130.4 1135.39   142.7 1135.58   150.9  1135.1   155.2 1134.48   159.1 1133.63
   163.2 1133.76   167.3 1134.58   171.4 1135.24   175.4 1136.63   187.7 1144.36
     200 1150.77     209 1157.06   212.3 1158.09   228.7 1158.76   236.8 1158.56
   240.9 1159.26     245 1161.76   249.1 1164.79   253.2 1166.98   266.5 1171.52
     280 1177.56   289.1 1180.37   322.5 1192.04   334.2 1195.43   369.6 1208.58
#Mann= 5 ,-1,0
       0      .1       0   155.2    .045       0   167.3      .1       0
  216.14     .06       0  226.14      .1       0
Bank Sta=155.2,167.3
XS Rating Curve= 0 ,0
Exp/Cntr(USF)=0,0
Exp/Cntr=0.3,0.1

Type RM Length L Ch R = 1 ,10702   ,554.9,556.9,557
XS GIS Cut Line= 4
1630179.74292589434609.1362079921630339.40835139434612.551511211
 1630447.8442286434635.6048079411630479.43578338434643.289240184
#Sta/Elev= 30
       0  1139.6     9.2 1139.27    32.4 1137.67    72.4 1136.24    84.4 1135.52
   100.4 1134.87   108.4 1134.17   112.4 1134.01   120.4 1134.05   144.4 1133.19
     185  1132.4     194  1131.8   205.4 1131.36   209.5 1130.51   213.6    1129
   217.7 1128.32     221 1128.99   234.5 1133.48   246.3 1140.55   250.4  1142.7
   258.6 1146.67   262.7 1149.48   266.7 1152.56   270.8 1154.54     275 1155.09
   279.1 1155.28   295.5 1155.39     298 1155.62   299.7 1155.85   303.1 1157.77
#Mann= 4 ,-1,0
       0     .05       0   169.7     .06       0   213.6    .045       0
     221     .06       0
Bank Sta=213.6,221
XS Rating Curve= 0 ,0
Exp/Cntr(USF)=0,0
Exp/Cntr=0.3,0.1

Type RM Length L Ch R = 1 ,10146   ,432.2,433.4,432.9
XS GIS Cut Line= 2
1630099.19285081435103.8018758621630433.37061918435213.052300137
#Sta/Elev= 30
       0 1178.72     5.2 1176.57    86.9 1130.12    89.3  1128.8    93.3 1127.37
     102 1125.57   114.6 1123.85   144.1 1122.75   177.7 1122.55   182.1    1122
   186.91120.678   194.6 1120.06   198.8 1120.23   201.1  1120.7     203 1121.16
   207.2 1123.28   211.4 1126.23     217  1130.7   228.2 1140.52   232.4 1144.74
   236.6 1147.37   240.8    1148   257.7 1148.76   261.9 1151.58   270.3 1160.01
   274.5 1163.04   296.3 1173.43   320.8 1184.22   333.4 1189.07   351.6 1194.59
#Mann= 5 ,-1,0
       0      .1       0     160     .06       0   186.9    .045       0
   201.1     .06       0     270      .1       0
Bank Sta=186.9,201.1
XS Rating Curve= 0 ,0
Exp/Cntr(USF)=0,0
Exp/Cntr=0.3,0.1

Type RM Length L Ch R = 1 ,9712    ,416.4,417.7,419
XS GIS Cut Line= 4
1629955.43150208435473.9161424061630010.07635359435515.753606841
1630217.55602416435596.8670582981630298.66947561435584.913497031
#Sta/Elev= 30
       0 1157.08    30.9 1142.58    50.9 1131.71    63.5 1124.29      71 1121.12
    77.2 1119.28    83.9 1118.55   105.4 1117.78   152.6 1118.07   178.4 1117.17
   206.9 1117.66   212.7 1116.97   218.51114.794   222.3 1113.89   225.6 1114.04
   228.5 1114.87   242.8  1118.4   247.1 1120.41   251.4 1123.49   259.3 1129.81
   264.3 1133.17   268.6 1133.97   285.8 1133.85   291.6 1135.69   302.3 1140.35
   306.3  1142.4   318.4 1150.18   326.5 1154.28   358.9 1168.74   373.6 1173.53
#Mann= 6 ,-1,0
       0      .1       0  118.82     .05       0  148.82      .1       0
   218.5    .045       0   228.5     .06       0  331.59      .1       0
#XS Ineff= 2 , 0
          148.96 1122.22
Permanent Ineff=
       F       F
Bank Sta=218.5,228.5
XS Rating Curve= 0 ,0
Exp/Cntr(USF)=0,0
Exp/Cntr=0.3,0.1

Type RM Length L Ch R = 1 ,9294    ,271.2,269.4,266.3
XS GIS Cut Line= 3
1629789.28778901435815.0885696021629980.08096268 435955.28465854
1630053.86837791435992.178366155
#Sta/Elev= 30
       0 1147.29    14.5 1141.64    22.7 1137.27    28.8  1133.8    40.3 1126.56
    48.2 1120.97    53.1 1117.07    57.4 1114.02    60.3 1112.51    63.1 1111.44
      68 1111.13   132.6  1110.6   137.5 1110.16   143.3 1107.69   147.5  1106.8
   151.8 1107.62   157.8 1110.87   162.3 1112.15   166.2 1112.51   177.6 1112.37
   180.5 1112.78   183.3 1113.68   187.2 1115.88   197.6 1124.38   203.3 1127.73
   231.8 1139.78   268.1  1153.2   272.6 1155.24   300.3 1169.77   319.3 1179.13
#Mann= 5 ,-1,0
       0      .1       0      90     .06       0   143.3    .045       0
   151.8     .06       0     210      .1       0
Bank Sta=143.3,151.8
XS Rating Curve= 0 ,0
Exp/Cntr(USF)=0,0
Exp/Cntr=0.3,0.1

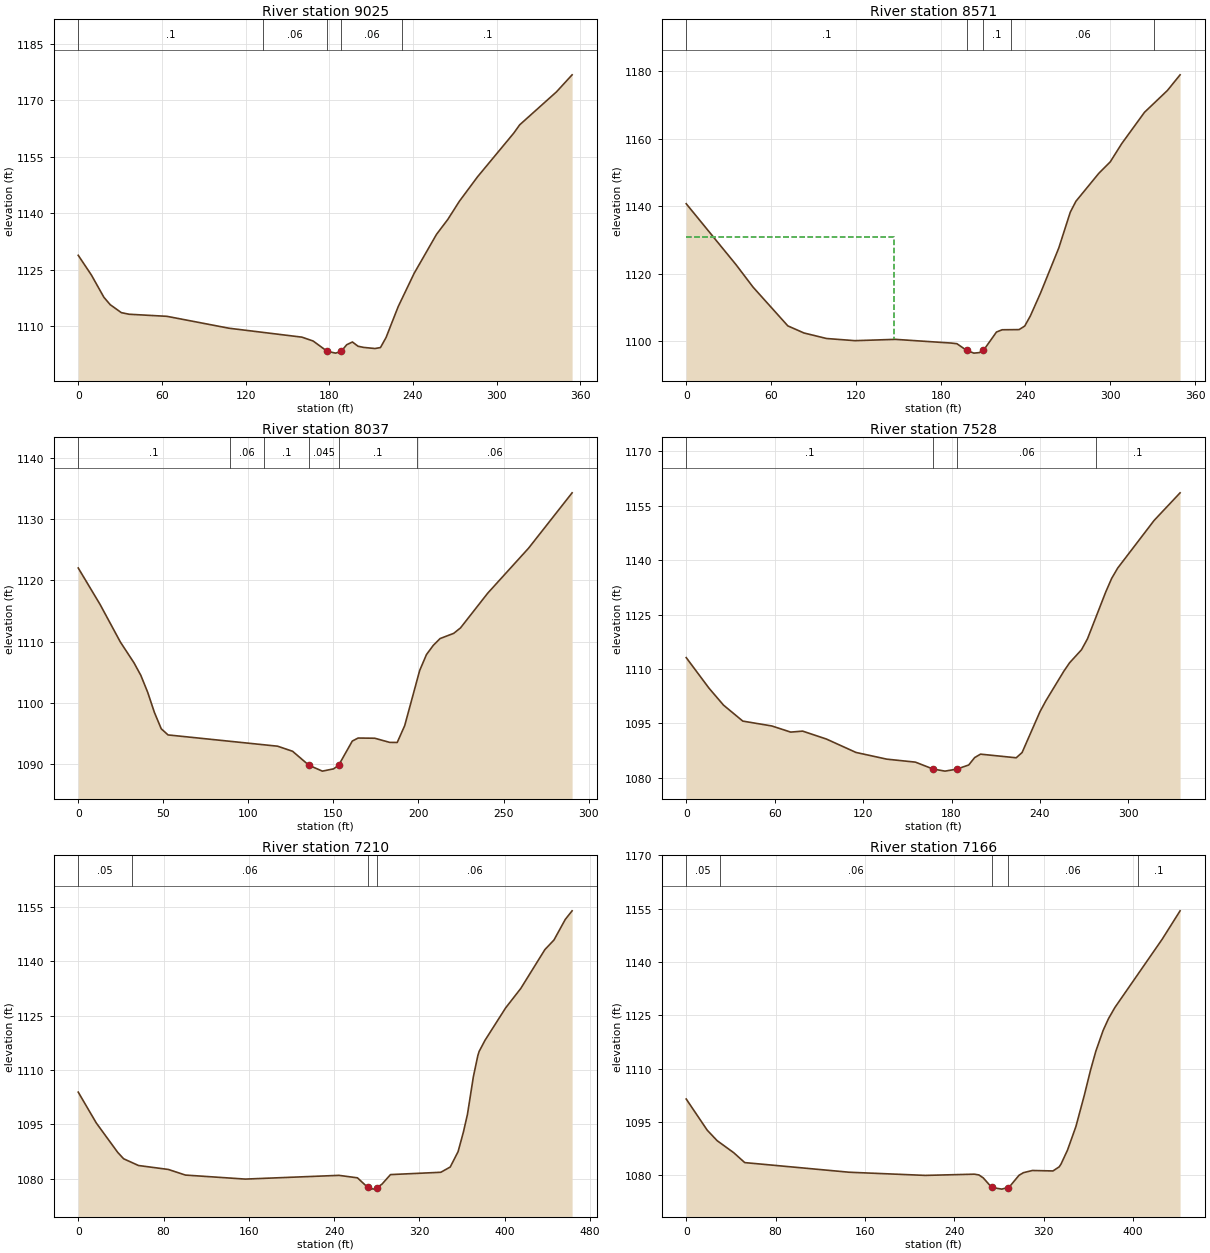
Type RM Length L Ch R = 1 ,9025    ,451.4,453.7,451.1
XS GIS Cut Line= 4
1629639.83542767436186.0173559651629730.51172814436138.373876056
1629895.72702138436156.0480702161629974.87667348436188.322685638
#Sta/Elev= 30
       0 1128.85     9.4 1123.64    18.4 1117.71    22.9 1115.75    30.9 1113.63
    36.5  1113.2    63.6 1112.65   108.1 1109.49   160.4 1107.12   168.4  1106.1
   178.5 1103.37   184.5 1102.88   188.5 1103.34   192.5 1105.11   196.6 1105.84
   200.6 1104.71   204.6  1104.4   212.7  1104.1   216.7 1104.36   220.7 1107.02
   229.4 1115.22   240.8 1124.03   256.9 1134.42     265 1138.38   273.3 1143.21
   286.3 1149.69   312.3  1161.3   316.5 1163.48   342.9 1172.24   354.1 1176.76
#Mann= 5 ,-1,0
       0      .1       0  132.43     .06       0   178.5    .045       0
   188.5     .06       0  232.43      .1       0
Bank Sta=178.5,188.5
XS Rating Curve= 0 ,0
Exp/Cntr(USF)=0,0
Exp/Cntr=0.3,0.1

Type RM Length L Ch R = 1 ,8571    ,531,534.9,536.6
XS GIS Cut Line= 3
1629628.92573921436516.1037768491629889.42799226436529.935754887
1629977.03051984436516.872220073
#Sta/Elev= 30
       0 1140.79    35.2 1122.76    47.3 1116.08    71.9  1104.6    83.3  1102.5
    99.3 1100.86   119.4 1100.22     148 1100.61   187.5 1099.51   191.5 1099.32
   198.31097.372   203.5 1096.53   207.5 1096.69   209.71097.438   211.5 1098.05
   219.5 1102.78   223.5 1103.45   235.5  1103.5   239.5 1104.56   243.5 1107.58
   250.7 1114.36   263.6  1127.7   271.7 1138.27   275.7 1141.52   291.9  1149.8
     300  1153.2   308.1 1158.59   324.2 1167.87   340.4 1174.33   349.4 1178.98
#Mann= 5 ,-1,0
       0      .1       0   198.3    .045       0   209.7      .1       0
     230     .06       0  330.87      .1       0
#XS Ineff= 2 , 0
          146.69 1130.89
Permanent Ineff=
       F       F
Bank Sta=198.3,209.7
XS Rating Curve= 0 ,0
Exp/Cntr(USF)=0,0
Exp/Cntr=0.3,0.1

Type RM Length L Ch R = 1 ,8037    ,511,508.3,502.6
XS GIS Cut Line= 4
1629571.31240199437005.7687401451629640.47229218 437004.91491434
1629760.00790485437059.5597658481629849.65961436437059.559765848
#Sta/Elev= 30
       0 1122.01    12.8 1116.08    24.8 1109.91    32.8 1106.52    36.8 1104.48
    40.8 1101.74    44.8 1098.42    48.8 1095.76    52.8 1094.76   117.2 1092.92
     126 1092.09   135.6 1089.81   143.5 1088.85   150.1 1089.22   153.1 1089.82
   161.1 1093.76   164.5 1094.25   174.3 1094.22   183.1 1093.54   187.5 1093.53
   191.9 1096.28   200.7 1105.28   204.7 1107.88   208.7 1109.38   212.7 1110.49
   220.7 1111.34   224.7 1112.23   240.7  1117.9   264.7 1125.24   290.3 1134.28
#Mann= 6 ,-1,0
       0      .1       0   89.17     .06       0  109.17      .1       0
   135.6    .045       0   153.1      .1       0  199.17     .06       0
Bank Sta=135.6,153.1
XS Rating Curve= 0 ,0
Exp/Cntr(USF)=0,0
Exp/Cntr=0.3,0.1

Type RM Length L Ch R = 1 ,7528    ,322,318.5,308.5
XS GIS Cut Line= 4
 1629587.5893215437506.0959598171629657.51765491437524.538597201
1629851.93379067437502.2537436951629917.25146473437486.884879209
#Sta/Elev= 30
       0 1113.14    15.5 1104.69    25.3 1100.04    38.4 1095.63    58.1 1094.29
    70.9  1092.6      79 1092.87    95.1 1090.69   115.2 1086.99   136.1 1085.14
   155.5 1084.32   167.5 1082.42   175.6 1081.84   183.6 1082.39   191.7 1083.54
   195.7 1085.57   199.7 1086.52   223.9 1085.52   227.9 1086.97     240  1098.2
     244 1101.21   256.1 1109.31   260.1  1111.7   268.2  1115.3   272.3 1118.35
   284.6 1131.18   288.7    1135   292.8 1137.84   317.5 1150.97   335.1 1158.57
#Mann= 4 ,-1,0
       0      .1       0   167.5    .045       0   183.6     .06       0
  278.01      .1       0
Bank Sta=167.5,183.6
XS Rating Curve= 0 ,0
Exp/Cntr(USF)=0,0
Exp/Cntr=0.3,0.1

Type RM Length L Ch R = 1 ,7210    ,46.8,43.6,43.2
XS GIS Cut Line= 4
1629814.42158172438038.4674049561629859.24638815438005.210290507
1629873.70600313437705.1732797211629951.78792401437632.152224084
#Sta/Elev= 30
       0 1103.91    16.9 1095.41      37 1087.29    42.6 1085.51    56.5 1083.66
    84.5 1082.57   100.5 1081.02   156.6 1079.91   244.5 1080.94   261.8 1080.26
  271.531077.608   276.7 1077.14   280.21077.573   284.8 1078.51   292.8 1081.15
     340 1081.79   348.8 1083.24   356.2 1087.49   361.2 1092.92     365 1097.82
   370.5 1108.14   374.7 1113.98   375.9 1115.13   381.4  1118.2   400.8 1127.17
     415 1132.54   437.6 1143.26   446.1  1145.9   456.7 1151.58   463.1 1153.95
#Mann= 4 ,-1,0
       0     .05       0      50     .06       0  271.53    .045       0
   280.2     .06       0
Bank Sta=271.53,280.2
XS Rating Curve= 0 ,0
Exp/Cntr(USF)=0,0
Exp/Cntr=0.3,0.1

Type RM Length L Ch R = 1 ,7166    ,152.1,158.5,162.6
XS GIS Cut Line= 4
1629833.57365277438060.2420109241629900.08788167438012.525281498
1629905.87172766437760.205000138 1629981.7847063437683.569040757
#Sta/Elev= 30
       0 1101.48    18.8 1092.72    27.7 1089.76    42.5 1086.39    52.4  1083.6
   145.9 1080.89   213.9    1080   257.9 1080.34     262 1080.13   265.9  1079.3
   273.5 1076.61   282.5 1076.14  287.761076.585   289.9    1077   297.9 1080.03
   301.9 1080.77   309.9 1081.38   328.3 1081.25   333.9 1082.41   335.6 1083.24
   341.3  1087.1   348.8  1093.7   356.3 1102.46   361.9 1109.55   366.7 1114.94
   373.2 1120.76     378 1124.07   383.7  1127.2   426.1 1146.43   442.1  1154.4
#Mann= 5 ,-1,0
       0     .05       0      30     .06       0   273.5    .045       0
  287.76     .06       0  404.25      .1       0
Bank Sta=273.5,287.76
XS Rating Curve= 0 ,0
Exp/Cntr(USF)=0,0
Exp/Cntr=0.3,0.1

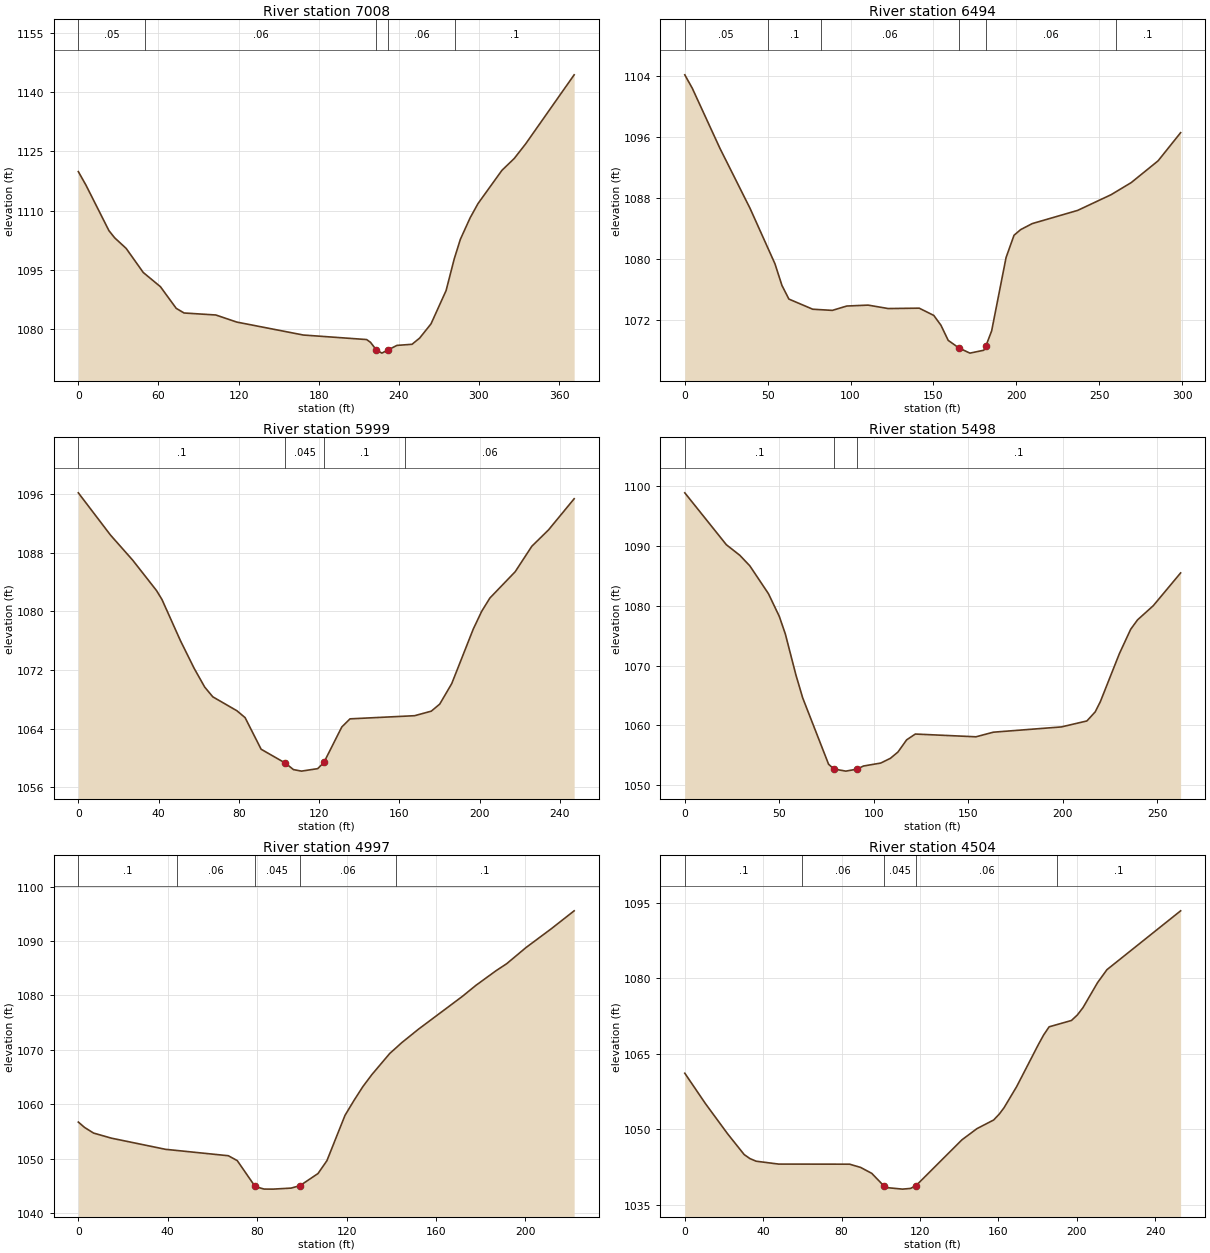
Type RM Length L Ch R = 1 ,7008    ,509.3,513.6,514.7
XS GIS Cut Line= 4
1629810.76390978438088.8620348151629868.39715161438066.577181309
1630043.60220676437873.6979320021630078.95059508437839.886430132
#Sta/Elev= 30
       0 1119.88     5.7 1116.46    22.9 1104.92    27.2 1103.09    35.8 1100.41
    48.6  1094.3    61.5 1090.68    73.3  1085.2    79.2 1084.02     103 1083.51
   118.6 1081.72   168.5 1078.43   215.9 1077.28   218.8 1076.58   223.11074.686
   227.3 1073.84   232.1 1074.69   238.6  1075.8   249.9 1076.08   255.6 1077.66
   264.1 1081.26   275.4 1089.71   281.5 1097.75   286.1 1102.72   293.4 1108.16
   299.3 1111.77   317.2  1120.2   326.4  1123.2   334.9 1126.88   371.3 1144.43
#Mann= 5 ,-1,0
       0     .05       0      50     .06       0   223.1    .045       0
   232.1     .06       0  281.79      .1       0
Bank Sta=223.1,232.1
XS Rating Curve= 0 ,0
Exp/Cntr(USF)=0,0
Exp/Cntr=0.3,0.1

Type RM Length L Ch R = 1 ,6494    ,491,494.6,495.8
XS GIS Cut Line= 4
1630103.76881847438420.8660719681630163.53662481438403.789555872
1630317.22526967438336.3373172921630385.53133406438326.091407634
#Sta/Elev= 30
       0 1104.14     4.5 1102.39    21.2 1094.51    39.4 1086.63    54.4 1079.38
    58.6 1076.55    62.8 1074.76    77.2 1073.43      89 1073.28    97.7 1073.85
   110.6 1073.97   122.7 1073.52   141.4 1073.57   150.2 1072.62   154.5 1071.34
   158.9 1069.35   165.41068.353     172 1067.68   180.4 1068.06   181.5 1068.55
   185.1 1070.59   193.8  1080.2   198.6 1083.12   202.6 1083.86   209.6 1084.65
     237 1086.38   257.2 1088.44   269.3 1090.02   285.5 1092.87   299.1 1096.56
#Mann= 6 ,-1,0
       0     .05       0      50      .1       0   82.16     .06       0
   165.4    .045       0   181.5     .06       0     260      .1       0
Bank Sta=165.4,181.5
XS Rating Curve= 0 ,0
Exp/Cntr(USF)=0,0
Exp/Cntr=0.3,0.1

Type RM Length L Ch R = 1 ,5999    ,504.3,501.8,497.4
XS GIS Cut Line= 4
1630198.95068854 438871.792234411630245.91110781438847.885111875
1630358.61611404438835.9315506081630436.31426228438812.878253878
#Sta/Elev= 30
       0 1096.19      16 1090.43    27.1 1086.99      39 1082.83    41.7 1081.61
    50.9 1075.99    57.7 1072.23      63 1069.65      67 1068.33      79 1066.43
    83.1 1065.49    91.1 1061.17   103.2 1059.27   107.2 1058.39   111.2 1058.18
   119.3 1058.52   122.4 1059.37   131.3 1064.21   135.4 1065.32   167.6 1065.75
   175.9 1066.37   180.1 1067.33   186.1 1070.14   196.8 1077.57     201    1080
   205.1 1081.82   217.7 1085.41     226 1088.89   234.3 1091.12   247.1 1095.38
#Mann= 4 ,-1,0
       0      .1       0   103.2    .045       0   122.4      .1       0
   162.7     .06       0
Bank Sta=103.2,122.4
XS Rating Curve= 0 ,0
Exp/Cntr(USF)=0,0
Exp/Cntr=0.3,0.1

Type RM Length L Ch R = 1 ,5498    ,494.6,500.8,502.3
XS GIS Cut Line= 4
1630396.39795826439347.7137543671630443.27299494439324.660457637
1630550.08660313439264.7218861391630628.46781201439225.531281699
#Sta/Elev= 30
       0 1098.88      22  1090.2    29.1 1088.44    34.4 1086.68    44.3    1082
      50 1078.23    53.2 1075.29    58.8 1068.44    62.4 1064.59    76.1  1053.5
    78.91052.707    85.2 1052.35    91.1 1052.68    94.5  1053.2   103.7  1053.7
   108.8 1054.49   112.8 1055.54   117.4 1057.58     122 1058.55   154.1 1058.09
   163.3 1058.86   199.3 1059.74   212.8 1060.74   217.2 1062.26   219.9 1063.95
     230    1072     236 1076.08   239.6 1077.64   247.9    1080   262.4 1085.49
#Mann= 3 ,-1,0
       0      .1       0    78.9    .045       0    91.1      .1       0
Bank Sta=78.9,91.1
XS Rating Curve= 0 ,0
Exp/Cntr(USF)=0,0
Exp/Cntr=0.3,0.1

Type RM Length L Ch R = 1 ,4997    ,501.9,492.6,488.4
XS GIS Cut Line= 4
 1630501.3744277 439751.508952581630545.17569148439746.898293234
1630642.76798097439738.4454177661630715.77008728439706.170802345
#Sta/Elev= 30
       0 1056.72     2.8 1055.73     6.8  1054.7    14.8 1053.76      39 1051.71
    67.1 1050.53    71.1 1049.63    78.91044.983    79.1 1044.87    83.1  1044.4
    87.1 1044.39    95.2 1044.58    99.2 1045.04   107.2 1047.25   111.2 1049.62
   119.3 1057.96   123.3 1060.69   127.3 1063.25   131.3 1065.44   139.3 1069.33
     142 1070.32   144.5 1071.26   152.2 1073.81   171.8 1079.83   177.8 1081.84
   186.9 1084.56   191.6 1085.83   200.3 1088.82   211.5 1092.24   221.8 1095.56
#Mann= 5 ,-1,0
       0      .1       0   44.04     .06       0    78.9    .045       0
    99.2     .06       0     142      .1       0
Bank Sta=78.9,99.2
XS Rating Curve= 0 ,0
Exp/Cntr(USF)=0,0
Exp/Cntr=0.3,0.1

Type RM Length L Ch R = 1 ,4504    ,506.1,499.4,499.8
XS GIS Cut Line= 3
  1630806.556219440205.8819773281630947.84987466440068.945394753
1630972.74743512440018.527834804
#Sta/Elev= 30
       0 1061.14    10.5 1055.13    21.9 1049.09    30.3    1045    33.2 1044.21
    36.4 1043.68    47.9 1043.11    84.1 1043.09    89.7 1042.45    95.4 1041.27
   101.41038.855   103.9 1038.41   111.1 1038.14   115.2 1038.28     118 1038.84
   141.4 1047.92   149.1 1050.15   157.6 1051.86   160.5 1053.05   162.9  1054.3
   169.3 1058.46   180.4 1066.82   183.1 1068.73   185.9 1070.35   197.3 1071.61
   200.3  1072.7   203.2 1074.17   210.6 1079.11   215.4 1081.69     253 1093.37
#Mann= 5 ,-1,0
       0      .1       0      60     .06       0   101.4    .045       0
     118     .06       0     190      .1       0
Bank Sta=101.4,118
XS Rating Curve= 0 ,0
Exp/Cntr(USF)=0,0
Exp/Cntr=0.3,0.1

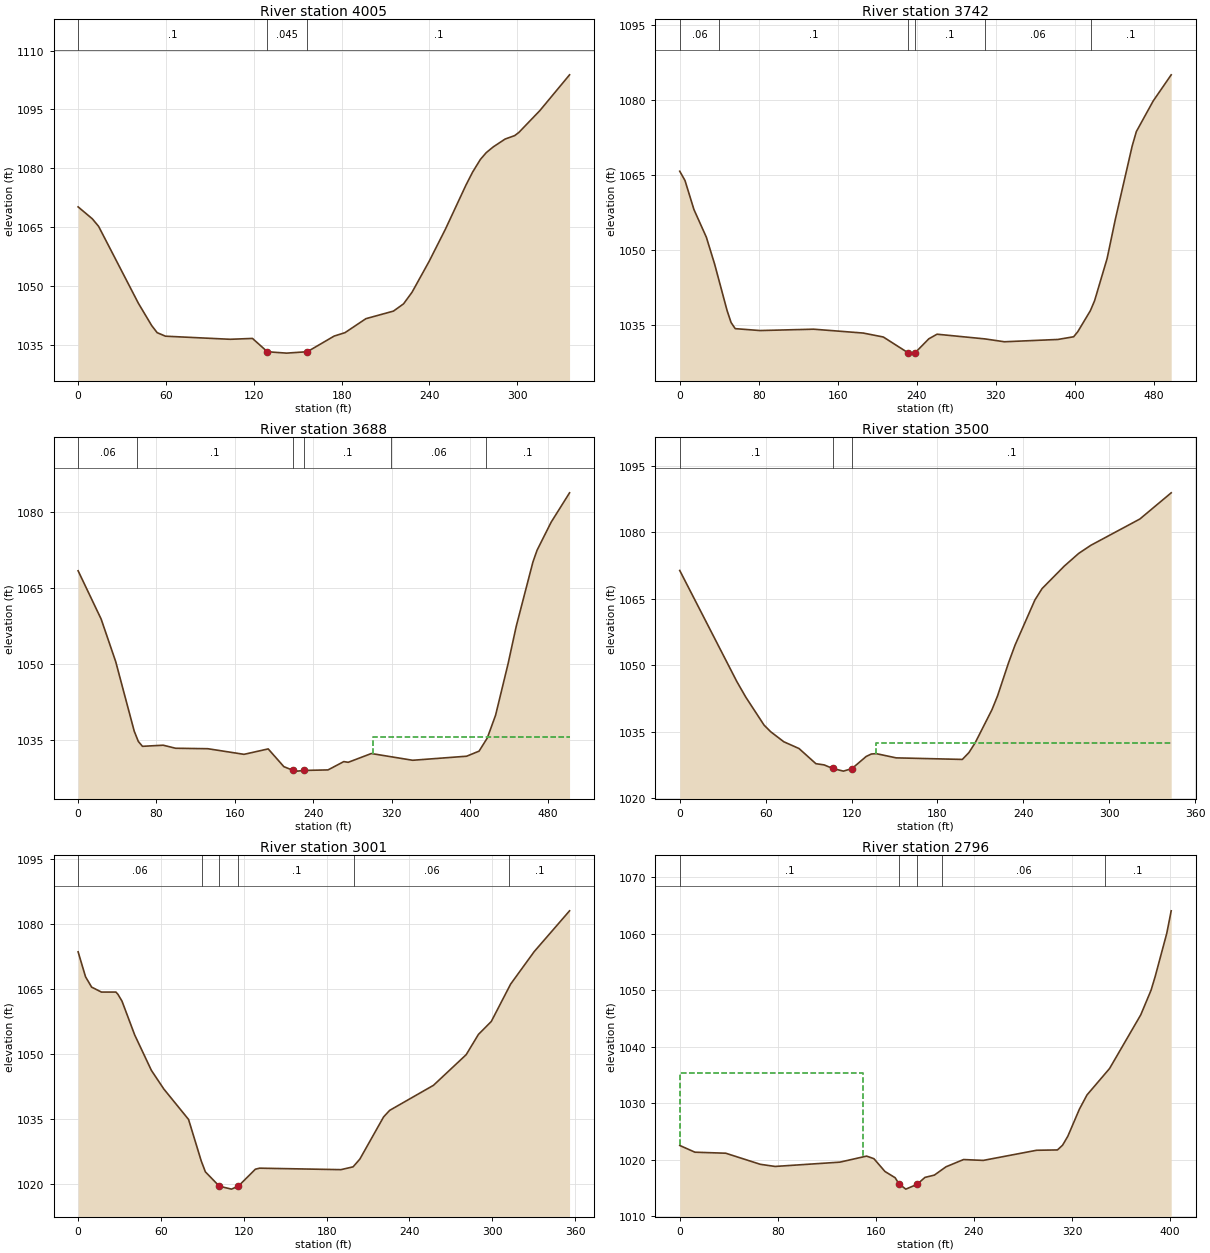
Type RM Length L Ch R = 1 ,4005    ,242.5,262.6,271.7
XS GIS Cut Line= 4
 1631043.8036378 440613.359852571631091.61788287440587.745078425
1631193.22315364440457.109730289 1631293.1207728440398.195749757
#Sta/Elev= 30
       0 1070.12     9.7 1067.08      14 1065.15    41.2 1045.51    50.3 1039.82
      54 1038.03    59.7 1037.13   103.9 1036.34   119.1 1036.56   129.3 1033.16
   142.4 1032.81   156.6 1033.17   174.9 1037.16   182.3 1038.03   196.6  1041.6
   215.4 1043.53   222.3 1045.38   228.1 1048.34   239.8 1056.24     251 1064.51
   264.9 1075.65   269.5 1079.01   274.8 1082.23   278.8 1083.96   283.6 1085.43
   291.7 1087.43   298.2  1088.3   301.1 1089.12   315.4 1094.68   335.7 1103.81
#Mann= 3 ,-1,0
       0      .1       0   129.3    .045       0   156.6      .1       0
Bank Sta=129.3,156.6
XS Rating Curve= 0 ,0
Exp/Cntr(USF)=0,0
Exp/Cntr=0.3,0.1

Type RM Length L Ch R = 1 ,3742    ,51.6,53.8,54.7
XS GIS Cut Line= 6
1631082.34658705440673.3741509151631215.92413813440632.606976235
1631193.37208405  440713.27393891631209.85243126 440767.05191401
1631235.00664543440781.7974878311631409.35137119440711.539165509
#Sta/Elev= 30
       0 1065.75     5.3  1063.9    14.4 1058.08    26.9 1052.59    35.3 1047.21
    47.9 1037.95      52 1035.52    56.2  1034.3    81.3 1033.92   135.7 1034.19
   185.9 1033.42   206.2 1032.63  230.891029.524   233.2 1029.41  238.611029.526
   252.3 1032.27   260.6 1033.19   309.2 1032.25   328.9 1031.68     383 1032.14
     399 1032.68   403.2  1033.7   415.9 1037.88   420.2 1039.88   432.9 1048.32
   441.3 1056.22   458.3  1070.8   462.5 1073.67   479.5 1079.77   497.8 1085.01
#Mann= 6 ,-1,0
       0     .06       0      40      .1       0  230.89    .045       0
  238.61      .1       0   309.2     .06       0  416.21      .1       0
Bank Sta=230.89,238.61
XS Rating Curve= 0 ,0
Exp/Cntr(USF)=0,0
Exp/Cntr=0.3,0.1

Type RM Length L Ch R = 1 ,3688    ,193,188.3,180.7
XS GIS Cut Line= 6
 1631081.9128937440695.0588182981631185.99929714 440659.49596379
1631163.44724306440740.1629264551631179.92759028440793.940901565
1631205.08180444440808.6864753861631411.51983793440728.019512721
#Sta/Elev= 30
       0 1068.44    23.5 1058.93    38.4 1050.52    57.3 1036.82    61.5 1034.79
    65.7 1033.83    86.9 1034.05    99.5 1033.45   132.4 1033.36   169.4 1032.25
   194.1 1033.32   210.1 1029.82   219.6 1029.08   223.7 1028.94  231.141029.078
   255.2 1029.18   271.3 1030.82   275.8 1030.68   299.4 1032.41   341.6 1031.08
   396.7 1031.88   409.4 1032.88   417.8 1035.47   426.3 1039.98     439 1050.09
   447.4 1057.53   464.4 1070.17   468.6 1072.48     483 1078.02   501.8 1083.81
#Mann= 6 ,-1,0
       0     .06       0      60      .1       0   219.6    .045       0
  231.14      .1       0  319.53     .06       0  416.54      .1       0
#XS Ineff= 2 , 0
                          301.51         1035.74
Permanent Ineff=
       F       F
Bank Sta=219.6,231.14
XS Rating Curve= 0 ,0
Exp/Cntr(USF)=0,0
Exp/Cntr=0.3,0.1

Type RM Length L Ch R = 1 ,3500    ,502.8,499.3,494.8
XS GIS Cut Line= 4
  1631179.228735440978.7145816051631220.21237363440950.538330046
1631393.53901201440850.6407108831631466.11420542440791.726730351
#Sta/Elev= 30
       0 1071.34    39.9 1046.28    46.2 1042.74    58.9 1036.47    63.5 1034.98
    72.7 1032.71    83.3 1031.19    95.1 1027.77   100.9 1027.49   106.8  1026.7
   114.3 1026.09   120.3 1026.66   130.2 1029.39   133.8 1029.95   137.3 1030.03
   151.2 1029.08   197.4 1028.73     202 1030.27   206.4  1032.5   218.1 1039.95
     222 1043.06   229.7 1050.55   234.3 1054.57   248.1  1064.7   253.1 1067.26
   268.6 1072.33   278.7  1075.2   287.2 1077.03   321.4 1082.95   343.3 1088.86
#Mann= 3 ,-1,0
       0      .1       0   106.8    .045       0   120.3      .1       0
#XS Ineff= 2 , 0
                          136.88         1032.53
Permanent Ineff=
       F       F
Bank Sta=106.8,120.3
XS Rating Curve= 0 ,0
Exp/Cntr(USF)=0,0
Exp/Cntr=0.3,0.1

Type RM Length L Ch R = 1 ,3001    ,211.1,204.4,193.9
XS GIS Cut Line= 3
1631570.60343194441333.4372344721631672.10992908441113.506490662
1631730.67136974441015.904089564
#Sta/Elev= 30
       0 1073.57     5.4  1067.8     9.8 1065.43    16.9 1064.29    27.4 1064.29
    28.9 1063.75    31.8 1062.19      41  1054.4    53.1 1046.23    62.1 1041.94
      80 1034.93    89.2 1025.35    92.2 1022.84   102.3 1019.53   111.1 1018.86
   116.11019.551   128.4 1023.45   131.4 1023.69   190.4 1023.35   199.2    1024
   204.1 1025.79   221.3 1035.51   225.7 1037.02   257.4 1042.79   281.1 1049.85
     290 1054.53   299.3 1057.51   313.3 1066.12   330.4 1073.62     356 1083.02
#Mann= 6 ,-1,0
       0     .06       0      90      .1       0   102.3    .045       0
   116.1      .1       0     200     .06       0  312.23      .1       0
Bank Sta=102.3,116.1
XS Rating Curve= 0 ,0
Exp/Cntr(USF)=0,0
Exp/Cntr=0.3,0.1

Type RM Length L Ch R = 1 ,2796    ,37.4,34.3,38
XS GIS Cut Line= 5
1631855.29340882441425.6546509781631869.75302379441318.010850589
1631799.06157279441253.7458951331631729.97674568441208.760426313
1631768.53571895441101.116625924
#Sta/Elev= 30
       0 1022.52    12.4 1021.33    37.5 1021.15    65.7 1019.19    77.8 1018.81
   130.6 1019.57   152.4 1020.64   158.4 1020.18   167.4 1017.92   175.7 1016.82
   178.8 1015.74   184.4  1014.8   193.61015.639     200 1016.87   207.7 1017.28
   217.2 1018.75   231.5 1020.03   247.6 1019.88   291.1 1021.67   308.1 1021.73
   312.3 1022.57   316.6 1024.16     326 1028.93   332.2 1031.45   350.6 1036.12
   376.1 1045.63   384.5 1049.99   387.8 1052.37   397.3 1060.04   400.9 1064.01
#Mann= 5 ,-1,0
       0      .1       0   178.8    .045       0   193.6      .1       0
  214.15     .06       0  346.59      .1       0
#XS Ineff= 2 , 0
          149.53 1035.38
Permanent Ineff=
       F       F
Bank Sta=178.8,193.6
XS Rating Curve= 0 ,0
Exp/Cntr(USF)=0,0
Exp/Cntr=0.3,0.1

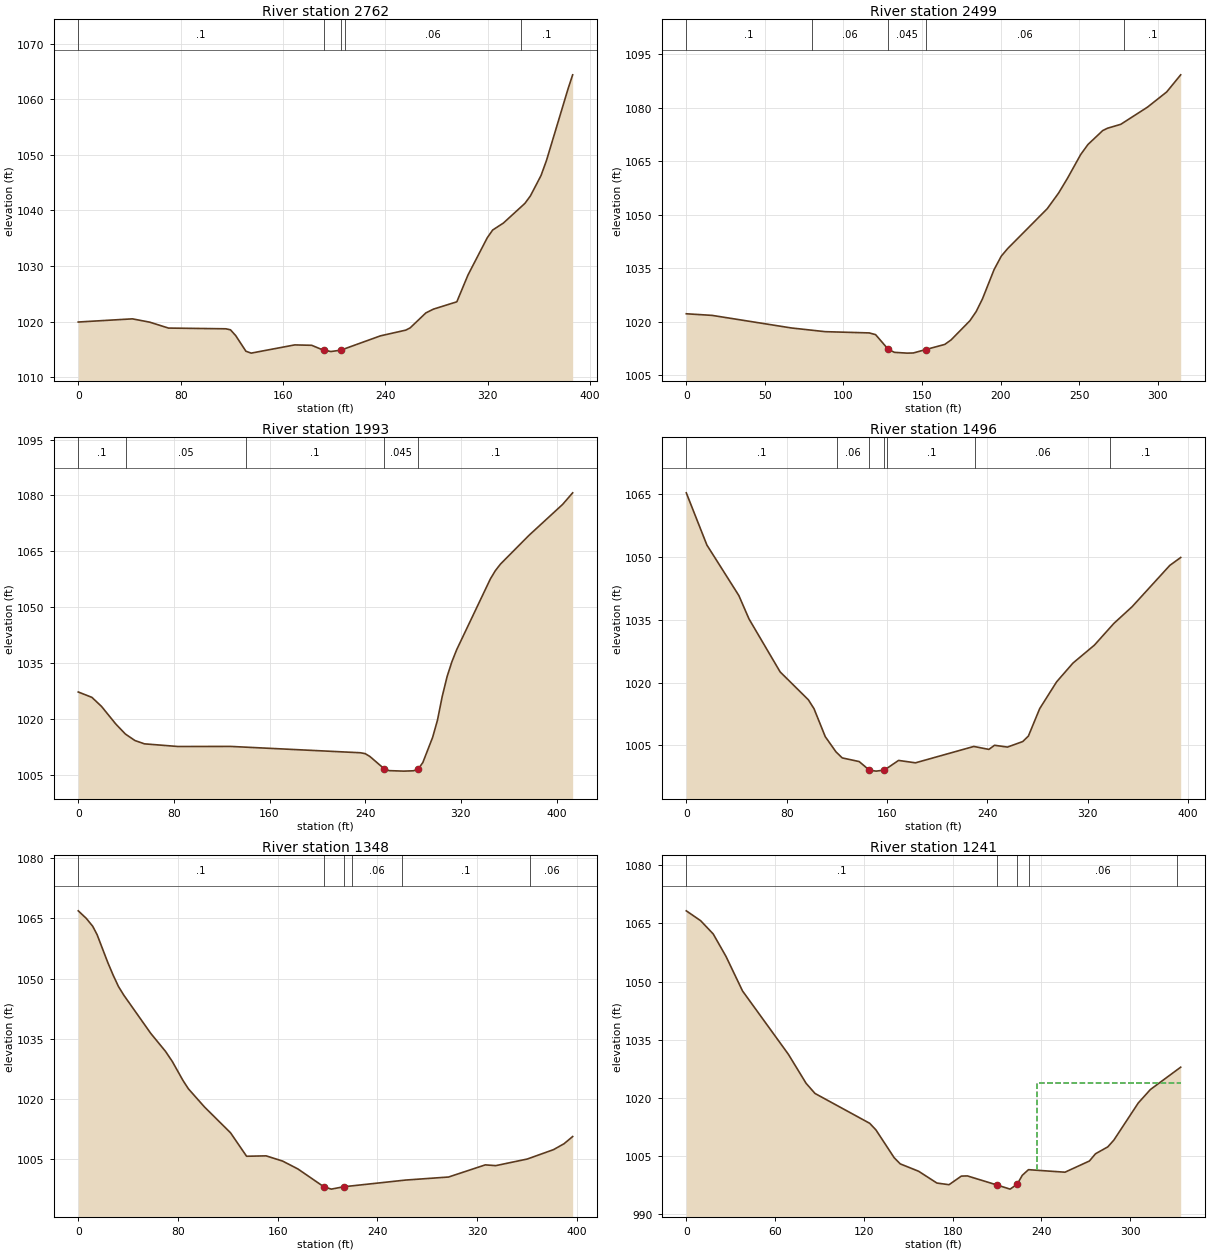
Type RM Length L Ch R = 1 ,2762    ,254.5,262.7,256
XS GIS Cut Line= 5
1631876.98283128441434.4910823541631894.65569403441297.124740066
 1631827.1774908441239.2862801551631771.74896672441199.120682995
1631799.86488473441113.166305072
#Sta/Elev= 30
       0 1019.92    42.3 1020.49    55.9 1019.89    70.5 1018.83   115.3  1018.7
   118.9 1018.52     123 1017.48     131 1014.66   135.1 1014.32   169.1  1015.8
   182.4 1015.73   191.8 1014.83   197.5 1014.61   205.1 1014.85   236.1 1017.43
   255.9 1018.46   259.3 1018.86   271.6 1021.56   277.4 1022.23   295.8 1023.56
   304.5 1028.38   319.6  1035.1   323.8 1036.48   332.2 1037.74     349 1041.28
   353.3 1042.63   361.6  1046.3   365.9 1049.04   382.7  1061.9   386.3 1064.42
#Mann= 5 ,-1,0
       0      .1       0   191.8    .045       0   205.1      .1       0
   208.5     .06       0  345.82      .1       0
Bank Sta=191.8,205.1
XS Rating Curve= 0 ,0
Exp/Cntr(USF)=0,0
Exp/Cntr=0.3,0.1

Type RM Length L Ch R = 1 ,2499    ,504.1,506.2,506.8
XS GIS Cut Line= 3
1632052.36443394441524.8904777481632055.77973716441316.556981374
1632091.64042096441216.659362211
#Sta/Elev= 30
       0  1022.2    16.4 1021.75      67 1018.21    88.4 1017.18   116.4 1016.83
   120.4 1016.35   128.51012.219   132.4 1011.38   140.4 1011.16   144.4  1011.2
   152.4 1012.17   164.4  1013.6   168.4 1014.85   180.4 1020.24   184.4 1022.82
   188.4 1026.38   195.8  1034.6   200.4 1038.39   204.4 1040.48   229.6 1051.68
   236.8 1056.05   242.4 1060.15   250.9 1066.89   255.5 1069.69   264.9  1073.6
   267.9 1074.25   276.4 1075.36   293.4 1080.18   305.6 1084.44   314.5 1089.24
#Mann= 5 ,-1,0
       0      .1       0      80     .06       0   128.5    .045       0
   152.4     .06       0  278.36      .1       0
Bank Sta=128.5,152.4
XS Rating Curve= 0 ,0
Exp/Cntr(USF)=0,0
Exp/Cntr=0.3,0.1

Type RM Length L Ch R = 1 ,1993    ,490.9,497.3,500.7
XS GIS Cut Line= 3
1632537.66219361 441683.929111311632540.50827962441531.189161782
1632570.86653046441272.195334322
#Sta/Elev= 30
       0 1027.24    11.4  1025.8    19.4 1023.39    31.4 1018.64    39.4 1015.96
    47.4 1014.21    55.4 1013.32    83.4 1012.61   127.4 1012.63     236 1010.93
     240 1010.69     244 1009.91   256.1 1006.57   260.1 1006.13   272.2    1006
   280.3 1006.09   284.3 1006.52   288.2 1008.32   296.4 1015.08   300.4 1019.64
   304.4 1026.03   308.5  1031.4   312.5 1035.36   316.5 1038.59   344.7  1057.6
   348.8 1059.78   353.1 1061.56   376.9 1069.26   405.1 1077.58   413.5 1080.69
#Mann= 5 ,-1,0
       0      .1       0      40     .05       0     140      .1       0
   256.1    .045       0   284.3      .1       0
Bank Sta=256.1,284.3
XS Rating Curve= 0 ,0
Exp/Cntr(USF)=0,0
Exp/Cntr=0.3,0.1

Type RM Length L Ch R = 1 ,1496    ,156.1,148,139.4
XS GIS Cut Line= 4
1632954.55328147441753.8811136671632966.12097345441684.474961775
1633070.23020129441482.0403520891633104.93327723441392.390739227
#Sta/Elev= 30
       0  1065.2    16.4 1052.77    41.9 1040.72      50 1035.14    74.8 1022.53
    97.3 1015.88   101.8 1013.76   110.8 1007.08   119.3 1003.48   124.3 1002.03
   137.8 1001.16   145.9999.1186   151.3  998.88   157.9  999.13   169.2 1001.43
   182.7 1000.86   229.2 1004.76   241.2 1004.06   245.7 1005.04     256 1004.61
   268.2 1005.93   272.7 1007.24   281.7 1013.77   295.2 1020.16   308.2 1024.62
   325.3  1028.9   340.8 1034.07   355.4 1038.07   385.4  1047.9   394.1 1049.79
#Mann= 7 ,-1,0
       0      .1       0  120.36     .06       0   145.9    .045       0
   157.9     .06       0  160.36      .1       0  230.36     .06       0
     338      .1       0
Bank Sta=145.9,157.9
XS Rating Curve= 0 ,0
Exp/Cntr(USF)=0,0
Exp/Cntr=0.3,0.1

Type RM Length L Ch R = 1 ,1348    ,99.5,106.9,113.9
XS GIS Cut Line= 6
1633143.00245377441826.5073106371633193.61110619441701.190647497
1633162.28194041441669.0581697691633127.73952685441633.712444268
1633071.50769083441604.793214313 1633104.4434805441505.985845299
#Sta/Elev= 30
       0  1066.9     6.4 1065.03    11.6 1063.05    15.1 1060.97    23.7 1054.01
      28 1050.86    32.3    1048    36.6 1045.84    58.2 1036.32      70 1031.85
    75.5 1029.31    84.1 1024.55    88.4  1022.5   101.3 1017.97   122.2 1011.53
   135.1 1005.67   150.8 1005.77     164 1004.47   176.3  1002.5  197.05998.0679
   203.1  997.47     213  998.06   262.7  999.73   297.2 1000.49   326.7 1003.52
   335.1 1003.33   360.4 1004.98   381.5 1007.33   389.9  1008.8   396.8 1010.59
#Mann= 6 ,-1,0
       0      .1       0  197.05    .045       0     213      .1       0
  220.03     .06       0  259.45      .1       0  362.68     .06       0
Bank Sta=197.05,213
XS Rating Curve= 0 ,0
Exp/Cntr(USF)=0,0
Exp/Cntr=0.3,0.1

Type RM Length L Ch R = 1 ,1241    ,245.8,260.8,266.4
XS GIS Cut Line= 3
1633158.19134705441848.288365288 1633219.3294911441779.771479716
1633278.35942329 441544.70585691
#Sta/Elev= 30
       0 1068.27     9.7 1065.72    18.2  1062.3    26.9 1056.46      38  1047.6
      69 1031.25      81 1023.75      87 1021.14     124 1013.43   128.2 1011.73
   140.5 1004.57   144.6 1002.97     157 1001.07   169.4  998.02   177.6  997.59
   185.9  999.81     190  999.86     210  997.52   218.9  996.45   223.7  997.73
   227.1 1000.01   231.3 1001.47     256 1000.82   272.5 1003.71   276.6 1005.57
   284.9 1007.35     289 1009.09   305.5 1018.67   313.7 1022.15   334.2 1027.92
#Mann= 5 ,-1,0
       0      .1       0     210    .045       0   223.7      .1       0
  231.83     .06       0  331.83      .1       0
#XS Ineff= 2 , 0
                          237.02         1023.85
Permanent Ineff=
       F       F
Bank Sta=210,223.7
XS Rating Curve= 0 ,0
Exp/Cntr(USF)=0,0
Exp/Cntr=0.3,0.1