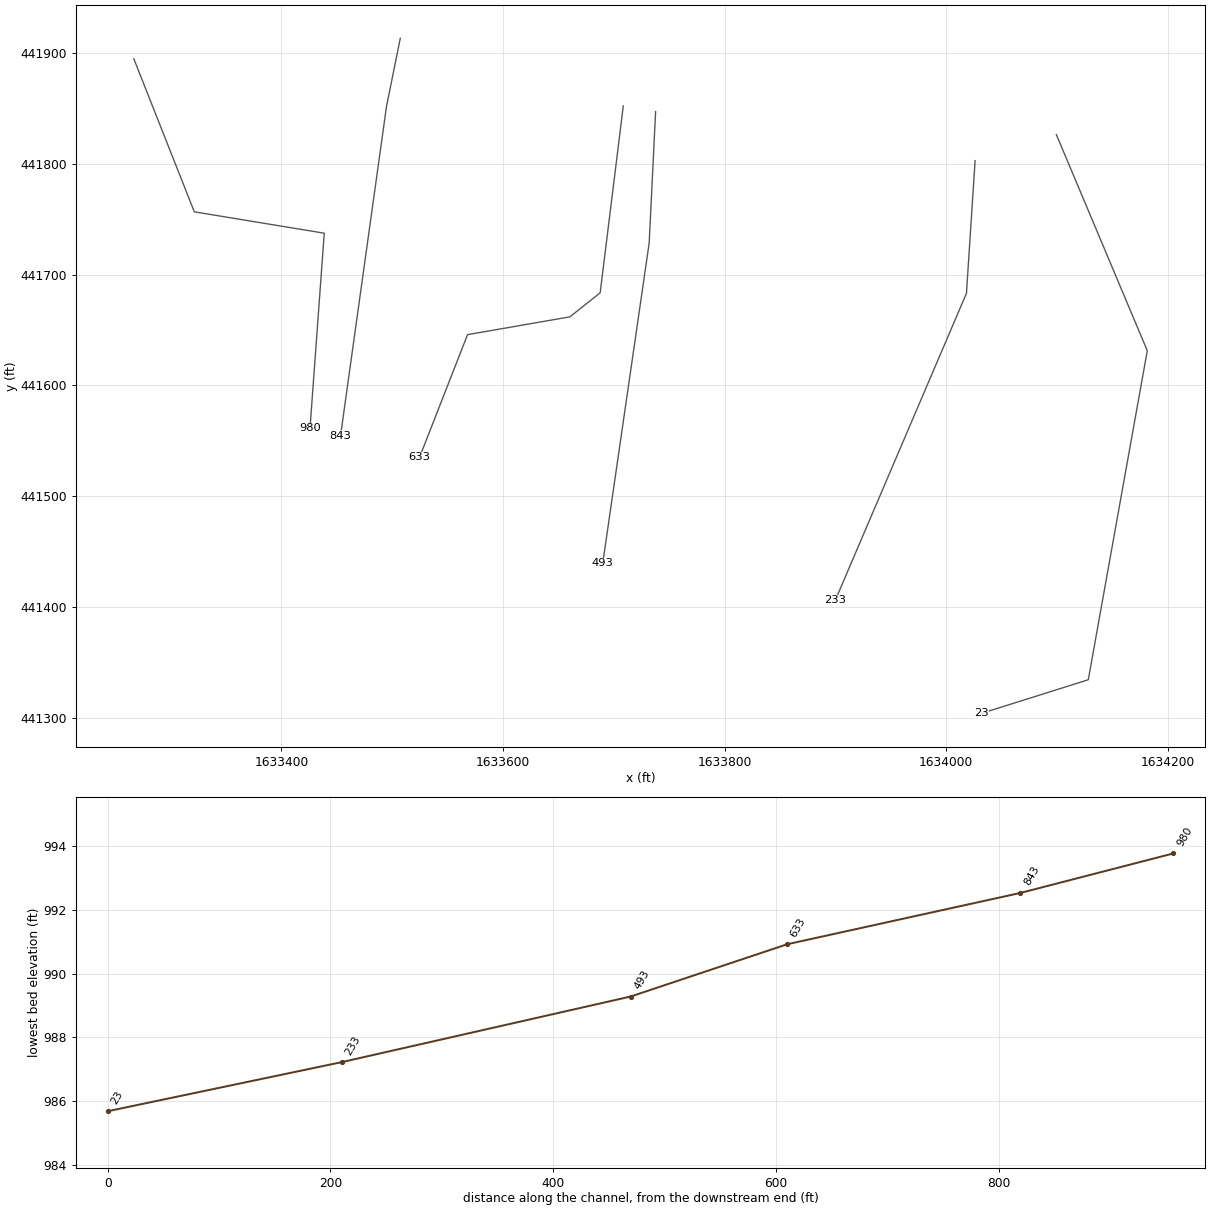
HEC-RAS study STEENERFK.prj: STEENERFK

--- STEENERFK.g01 (geometry) --- (continued)

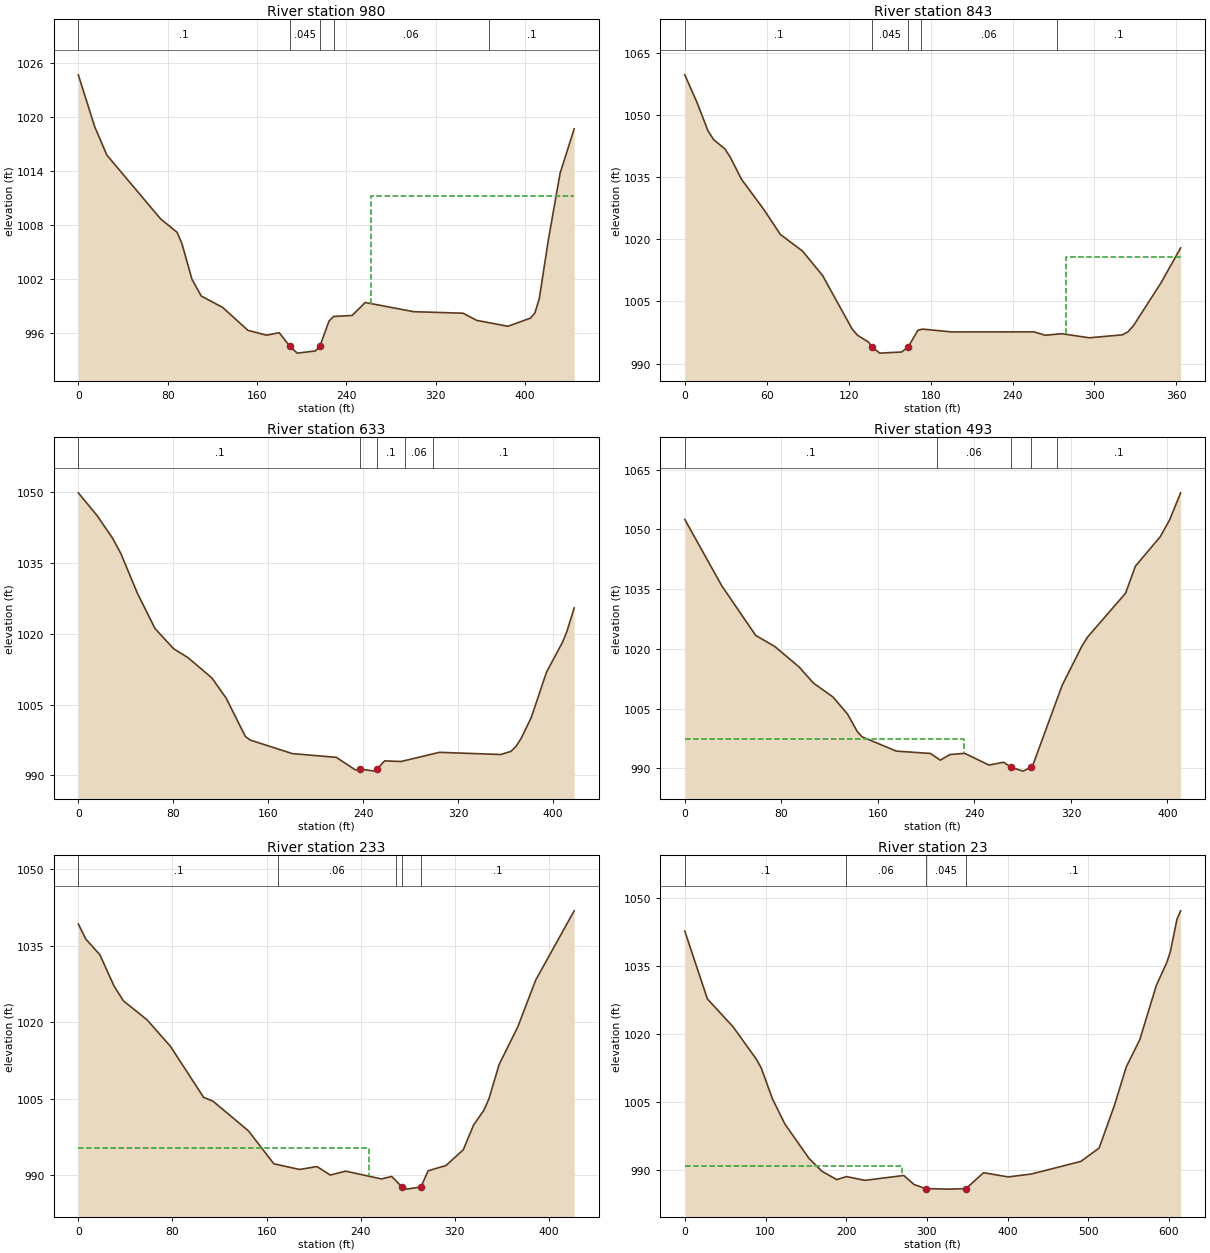
Type RM Length L Ch R = 1 ,980     ,154,137.4,114.9
XS GIS Cut Line= 4
1633266.71249302441894.7888258091633321.33770516441756.619171578
1633438.62124887441737.3396849411633425.76825778 441561.41436938
#Sta/Elev= 30
       0 1024.66    14.7 1018.88    25.6 1015.74    73.7 1008.66    88.4 1007.18
    92.7 1005.94   101.7 1001.97     110 1000.11   129.2  998.84   151.8   996.3
   168.5  995.76   179.8  996.04   189.4  994.51     196  993.77   212.2  994.01
   216.2  994.54   224.4  997.33   228.4  997.84   245.1  997.95   256.8  999.39
   300.2  998.37   344.4   998.2   356.5  997.41   384.5  996.75   404.6  997.65
   408.6  998.21   412.6  999.82   420.6 1006.26   431.2 1013.73   443.8 1018.66
#Mann= 5 ,-1,0
       0      .1       0   189.4    .045       0   216.2      .1       0
  228.58     .06       0  367.43      .1       0
#XS Ineff= 2 , 0
                          262.04         1011.23
Permanent Ineff=
       F       F
Bank Sta=189.4,216.2
XS Rating Curve= 0 ,0
Exp/Cntr(USF)=0,0
Exp/Cntr=0.3,0.1

Type RM Length L Ch R = 1 ,843     ,222.3,209.4,199.4
XS GIS Cut Line= 3
1633507.23700019441913.2189073111633494.78821996441851.666605042
1633453.29228584441554.279077226
#Sta/Elev= 30
       0 1059.69     8.9 1053.05      17 1046.17    21.1 1044.05    29.3 1041.84
    33.3 1039.82    41.5 1034.49    57.8 1027.23      70 1021.17    86.2 1017.16
   100.9 1011.26   122.5  998.38   126.5  996.84   134.6  995.19     137994.0602
   142.7  992.53   158.8   992.8   163.6  994.03   170.7  998.04   174.3  998.33
   195.2  997.65   255.8  997.66   263.9  996.84     276  997.22   296.2  996.23
   320.4  996.94   324.4  997.64   328.5  999.12   348.7 1009.48   363.1 1017.92
#Mann= 5 ,-1,0
       0      .1       0     137    .045       0   163.6      .1       0
   172.8     .06       0   272.8      .1       0
#XS Ineff= 2 , 0
                          279.22         1015.78
Permanent Ineff=
       F       F
Bank Sta=137,163.6
XS Rating Curve= 0 ,0
Exp/Cntr(USF)=0,0
Exp/Cntr=0.3,0.1

Type RM Length L Ch R = 1 ,633     ,129.9,140.5,149.1
XS GIS Cut Line= 5
1633708.53406179 441852.213292821633687.64795126441683.517784747
1633660.33534519 441661.828362281633567.95447173441645.762123416
1633524.57562679441534.905075254
#Sta/Elev= 30
       0 1049.86    15.8 1045.04    28.8 1040.27    35.9 1036.97    49.7 1028.63
    64.6 1021.12    80.3 1016.84    92.4 1014.95   112.5 1010.66   124.6 1006.36
   140.7  998.26   144.8   997.5   180.3  994.63   217.3  993.84   233.5  991.17
   237.6  991.34   249.7  990.92  251.79991.3635     258  993.09   271.9  992.96
   304.2   994.9   355.8  994.44   364.4   995.1   368.7  996.16     373  997.83
   381.6  1002.3   394.4 1011.87     408 1018.27   411.6  1020.5   417.7 1025.48
#Mann= 5 ,-1,0
       0      .1       0   237.6    .045       0  251.79      .1       0
  274.86     .06       0  298.63      .1       0
Bank Sta=237.6,251.79
XS Rating Curve= 0 ,0
Exp/Cntr(USF)=0,0
Exp/Cntr=0.3,0.1

Type RM Length L Ch R = 1 ,493     ,262.1,259.6,258
XS GIS Cut Line= 3
1633737.68938102441847.1368346621633731.90553503441728.567991845
1633689.97265159441439.375692293
#Sta/Elev= 30
       0 1052.52    30.6 1035.88    58.7  1023.4    74.7 1020.57    94.7 1015.46
   106.7 1011.38   122.8 1007.91   134.9  1003.6     143  999.19     147  997.89
   175.3  994.31   203.6  993.72   211.7  992.04   219.8  993.45   231.9  993.75
   252.1   990.8   264.2  991.52   270.3  990.26   270.3  990.24   280.4  989.28
   286.8990.2314   288.5  990.83   312.7 1010.82   328.9 1020.59   333.9 1023.01
   365.3    1034   373.4 1040.77   393.9 1048.14   401.7 1052.35   410.9 1059.21
#Mann= 5 ,-1,0
       0      .1       0  208.71     .06       0   270.3    .045       0
   286.8     .06       0  308.71      .1       0
#XS Ineff= 2 , 0
          231.13  997.28
Permanent Ineff=
       F       F
Bank Sta=270.3,286.8
XS Rating Curve= 0 ,0
Exp/Cntr(USF)=0,0
Exp/Cntr=0.3,0.1

Type RM Length L Ch R = 1 ,233     ,210.6,210.1,209.5
XS GIS Cut Line= 3
1634026.07461531441802.8055188421634018.26642322441683.079906827
1633899.84217656441405.889087707
#Sta/Elev= 30
       0 1039.25     6.3 1036.31    18.3 1033.22    30.3 1027.09    38.3 1024.17
    58.4 1020.45    78.4  1015.2   106.5 1005.22   114.5 1004.47   144.5  998.67
   166.2  992.19     188  991.08   202.8  991.65   214.1  989.98   227.1  990.75
   257.6  989.22   266.3  989.71     275  987.67   279.3  987.22   291.2  987.65
   297.3  990.82   312.5  991.86   327.2  994.95   335.9  999.79   344.6 1002.67
   348.9  1004.9   357.6 1011.65   373.5 1019.06   388.7 1028.24   421.4 1041.83
#Mann= 5 ,-1,0
       0      .1       0  169.98     .06       0  269.98      .1       0
     275    .045       0   291.2      .1       0
#XS Ineff= 2 , 0
          246.94  995.22
Permanent Ineff=
       F       F
Bank Sta=275,291.2
XS Rating Curve= 0 ,0
Exp/Cntr(USF)=0,0
Exp/Cntr=0.3,0.1

Type RM Length L Ch R = 1 ,23      ,,,
XS GIS Cut Line= 4
1634099.40727782441826.3468104511634181.48493274441631.264047493
1634128.23245459441334.2770983131634031.83502141441303.929758236
#Sta/Elev= 30
       0 1042.69      28 1027.71      60 1021.51    88.8 1014.35    94.7 1012.46
   108.8 1005.55   124.1 1000.05   153.8   992.5   169.9  989.63   188.2  987.79
   200.5  988.45   223.2  987.62   271.3   988.7   284.1   986.7  298.29   985.8
   328.2  985.68   348.5   985.8   370.2  989.31   400.7  988.38   429.8  989.03
   490.8  991.81   513.4  994.75   532.5 1004.25     547 1012.66   563.8 1018.71
   584.3 1030.69   597.4 1035.82   601.6 1038.08   609.9 1045.33   614.4 1047.17
#Mann= 4 ,-1,0
       0      .1       0     200     .06       0  298.29    .045       0
   348.5      .1       0
#XS Ineff= 2 , 0
          269.23  990.77
Permanent Ineff=
       F       F
Bank Sta=298.29,348.5
XS Rating Curve= 0 ,0
Exp/Cntr(USF)=0,0
Exp/Cntr=0.3,0.1
LCMann Table=0

Chan Stop Cuts=-1
Use User Specified Reach Order=0
Composite Channel Slope=5